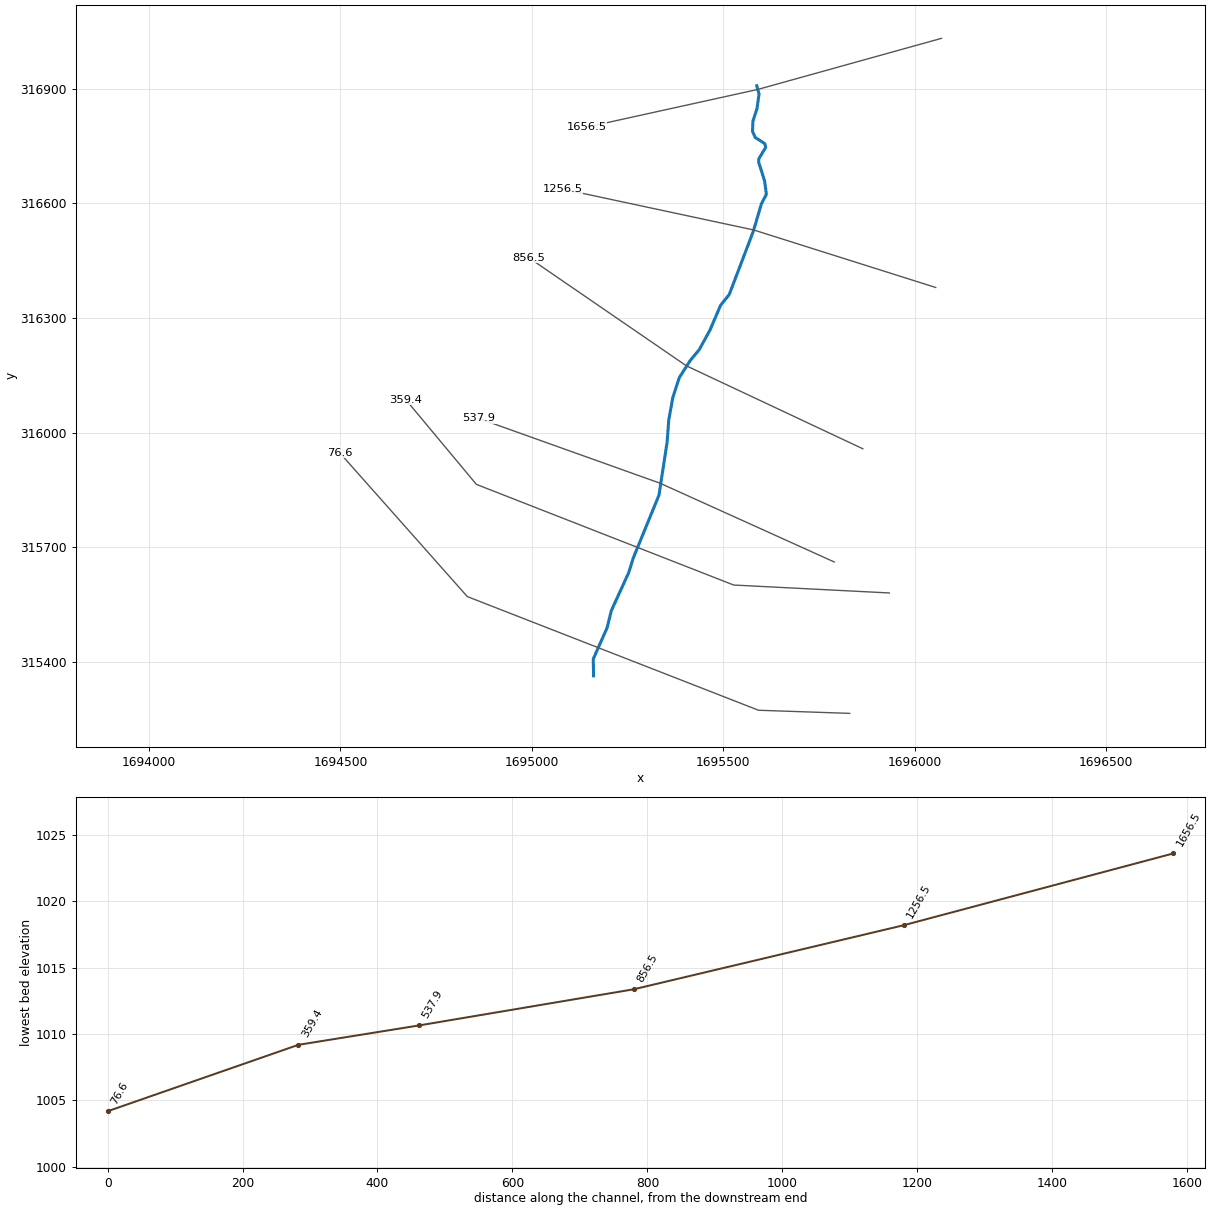
--- LRkcpRnTr.prj (project) ---

Proj Title=LRkcpRnTr
Current Plan=p01
Geom File=g01
Flow File=f01
Plan File=p01
DSS Export Rating Curves=0
DSS Export Rating Curve Sorted=0
DSS Export Volume Flow Curves=0
DXF OffsetX=0
DXF OffsetY=0
DXF ScaleX=0
DXF ScaleY=0

--- LRkcpRnTr.p01 (plan) ---

Plan Title=Floodplain
Program Version=4.00
Geom File=g01
Flow File=f01
K Sum by GR=0
Std Step Tol=0.01
Critical Tol=0.01
Num of Std Step Trials=20
Max Error Tol=0.3
Flow Tol Ratio=0.001
Split Flow NTrial=30
Split Flow Tol=0.02
Split Flow Ratio=0.02
Log Output Level=0
Friction Slope Method=1
Unsteady Friction Slope Method=2
Unsteady Bridges Friction Slope Method=1
Global Log Level=0
CheckData=False
Run HTab=0
Run UNet=0
Run PostProcess=0
UNET Theta=0
UNET Theta Warmup=0
UNET ZTol=0
UNET ZSATol=0
UNET MxIter=0
UNET MaxInSteps=0
UNET DtIC=0
UNET DtMin=0
UNET MaxCRTS=0
UNET WFStab=0
UNET SFStab=0
UNET WFX=0
UNET SFX=0
UNET DSS MLevel=0
UNET DZMax Abort=0
UNET Convert EG Bridges=0
UNET Use Existing IB Tables=0
UNET Froude Limit=0
UNET Froude Power=0
Write IC File=0
Echo Input=False
Echo Output=False
Write Detailed=0

--- LRkcpRnTr.f01 (steady flow) ---

Flow Title=NFF Regression Equation
Program Version=4.00
Number of Profiles=1
Profile Names=P100yr
River Rch & RM=LRkcpRnTr,Main      ,1656.5
734.7888
River Rch & RM=LRkcpRnTr,Main      ,359.4
755.7722
River Rch & RM=LRkcpRnTr,Main      ,76.6
1276.502
Boundary for River Rch & Prof#=LRkcpRnTr,Main      ,1
Up Type=0
Dn Type=3
Dn Slope=0.012677

--- LRkcpRnTr.g01 (geometry) ---

Geom Title=USGS 3m DEM
Program Version=4.00

River Reach=LRkcpRnTr     ,Main
Reach XY= 30
     1695587.201      316907.918     1695593.240      316886.248
     1695587.914      316848.242     1695577.257      316815.208
     1695576.191      316788.569     1695583.296      316772.586
     1695608.161      316756.603     1695610.647      316746.656
     1695592.531      316716.466     1695592.177      316708.294
     1695607.804      316658.568     1695612.423      316623.757
     1695599.278      316598.536     1695577.967      316526.075
     1695515.452      316361.619     1695492.721      316333.203
     1695465.014      316268.203     1695437.308      316217.764
     1695413.154      316188.282     1695385.094      316144.235
     1695368.044      316092.022     1695357.389      316032.704
     1695353.126      315975.162     1695331.814      315836.279
     1695264.681      315671.821     1695252.959      315633.814
     1695207.496      315534.359     1695196.482      315489.605
     1695160.252      315407.552     1695160.964      315363.509

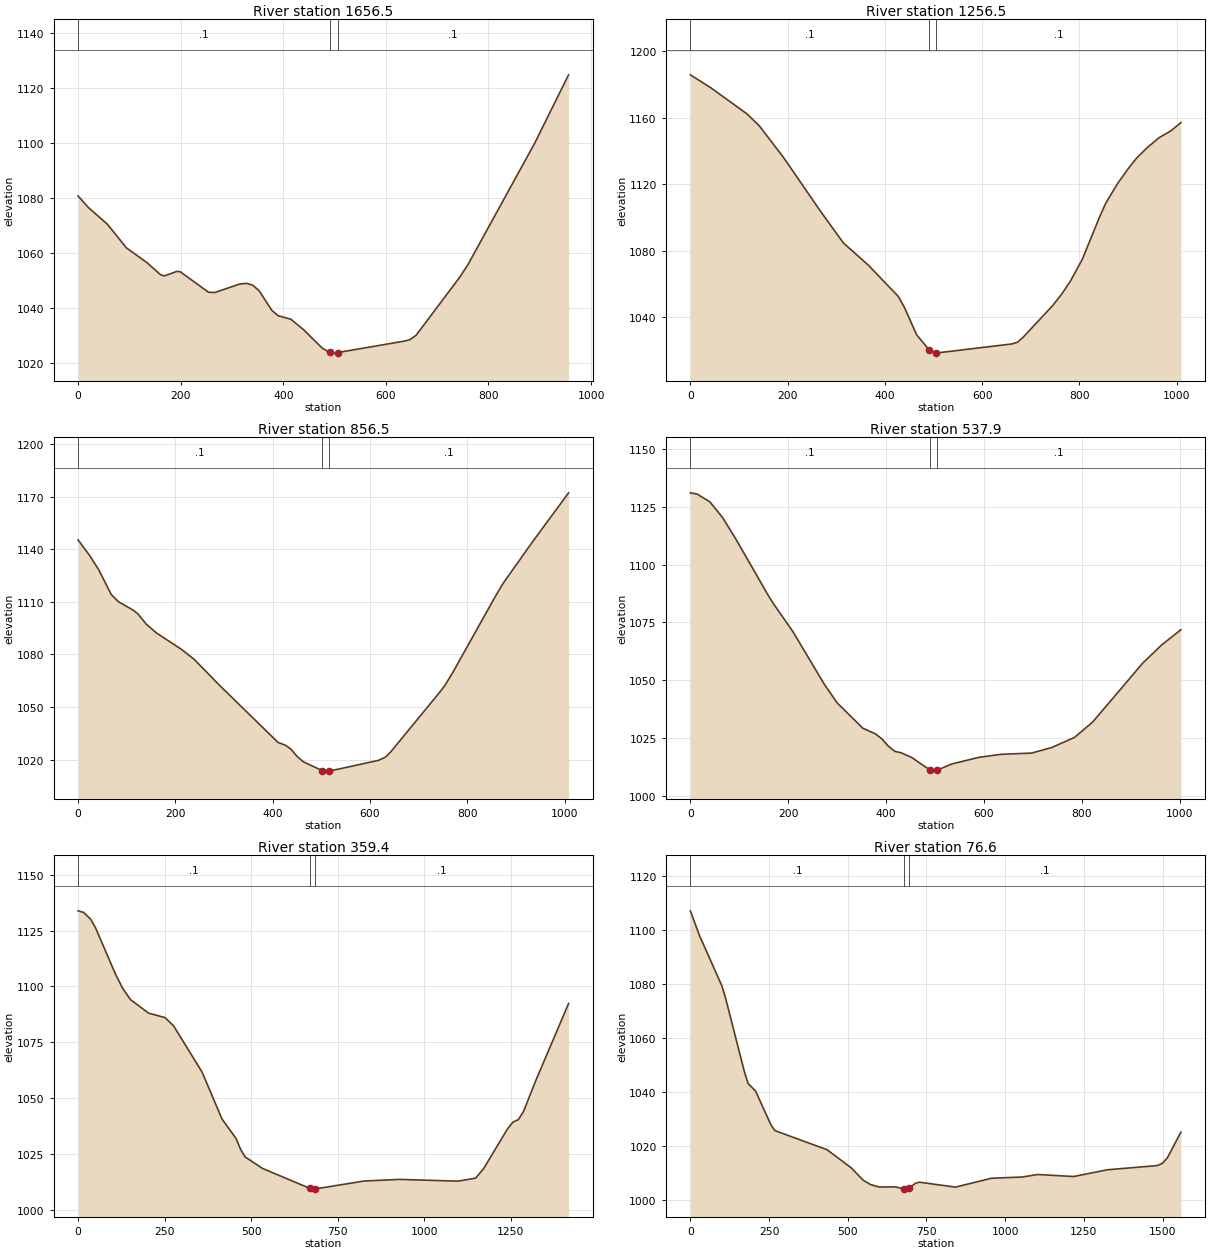
Type RM Length L Ch R = 1 ,1656.5,414.297,400,386.147
XS GIS Cut Line= 3
     1696069.925      317032.062     1695589.886      316898.285
     1695142.770      316799.553
#Sta/Elev= 30
       0 1080.76    20.3 1076.49    57.2 1070.47    94.2 1061.89   134.1 1056.54
   160.7 1052.13   168.2 1051.68   192.8 1053.33   199.3 1053.19   254.4 1045.73
   266.7 1045.66   314.9 1048.72   328.4 1048.97   340.7 1048.31   353.0 1046.28
   377.7 1039.18   390.0 1037.21   414.7 1035.96   439.3 1032.19   476.3 1025.39
   490.8 1023.86   500.9 1023.62   505.8 1023.82   634.6 1027.94   646.8 1028.49
   659.0 1030.12   744.1 1051.23   760.6 1055.97   890.0 1099.86   956.2 1124.76
#Mann= 3 , 0 , 0
       0     0.1       0   490.8   0.045       0   505.8     0.1       0
Bank Sta=   490.8,   505.8
Exp/Cntr=0.3,0.1

Type RM Length L Ch R = 1 ,1256.5,402.98,400,391.184
XS GIS Cut Line= 3
     1696054.746      316379.940     1695579.266      316530.490
     1695080.437      316637.507
#Sta/Elev= 30
       0 1185.86    41.9 1178.08   116.0 1162.43   141.5 1155.23   190.8 1136.39
   267.3 1103.83   314.6 1084.62   365.7 1071.29   427.7 1052.36   440.4 1045.66
   465.3 1029.27   491.2 1020.16   502.6 1018.20   506.2 1018.28   660.4 1023.70
   672.6 1024.72   684.0 1027.62   745.4 1046.93   764.0 1053.86   781.9 1061.71
   806.2 1074.76   842.6 1100.90   854.7 1108.68   879.0 1120.52   902.3 1129.99
   917.7 1135.66   939.7 1142.00   963.7 1147.94   988.3 1152.13  1008.9 1157.08
#Mann= 3 , 0 , 0
       0     0.1       0   491.2   0.045       0   506.2     0.1       0
Bank Sta=   491.2,   506.2
Exp/Cntr=0.3,0.1

Type RM Length L Ch R = 1 ,856.5,318.377,318.571,324.078
XS GIS Cut Line= 3
     1695864.292      315957.827     1695403.621      316174.801
     1694992.485      316457.458
#Sta/Elev= 30
       0 1145.43    24.7 1136.12    42.6 1128.28    68.2 1114.22    83.0 1110.11
   113.9 1105.17   122.9 1103.16   140.7 1097.15   161.7 1092.14   212.1 1082.99
   238.9 1077.14   291.1 1062.27   411.1 1029.73   426.2 1028.17   437.3 1025.97
   450.4 1021.67   463.6 1018.61   501.7 1013.68   512.8 1013.37   516.7 1013.41
   617.5 1019.52   632.0 1021.40   643.2 1024.58   743.4 1058.46   754.2 1062.41
   771.3 1070.27   856.7 1112.69   873.7 1120.64   933.5 1144.10  1008.1 1172.27
#Mann= 3 , 0 , 0
       0     0.1       0   501.7   0.045       0   516.7     0.1       0
Bank Sta=   501.7,   516.7
Exp/Cntr=0.3,0.1

Type RM Length L Ch R = 1 ,537.9,177.248,178.521,178.171
XS GIS Cut Line= 3
     1695789.766      315661.449     1695334.254      315867.839
     1694860.977      316037.240
#Sta/Elev= 30
       0 1131.09    13.6 1130.57    39.7 1127.23    65.8 1120.39    93.8 1110.80
   157.0 1087.50   170.1 1083.02   209.2 1071.15   274.3 1048.07   300.1 1040.18
   352.5 1029.23   378.6 1026.74   391.6 1024.58   404.7 1021.46   417.7 1019.21
   430.7 1018.59   452.6 1016.53   489.3 1011.20   495.9 1010.64   504.3 1011.03
   533.9 1013.70   590.2 1016.63   634.8 1017.91   697.8 1018.45   738.8 1020.86
   785.3 1025.23   822.4 1031.87   924.8 1057.39   962.6 1065.09  1002.8 1071.85
#Mann= 3 , 0 , 0
       0     0.1       0   489.3   0.045       0   504.3     0.1       0
Bank Sta=   489.3,   504.3
Exp/Cntr=0.3,0.1

Type RM Length L Ch R = 1 ,359.4,282.776,282.774,282.772
XS GIS Cut Line= 4
     1695933.624      315580.390     1695527.062      315601.133
     1694854.989      315864.569     1694670.377      316086.519
#Sta/Elev= 30
       0 1133.86    15.9 1133.18    36.6 1130.05    49.8 1126.48   108.9 1105.25
   129.0 1099.12   151.6 1094.06   204.0 1088.01   251.6 1086.02   276.0 1082.34
   358.6 1061.57   416.1 1040.55   456.7 1031.87   469.8 1026.98   482.6 1023.63
   533.6 1018.41   669.5 1009.55   673.9 1009.18   684.5 1009.25   826.9 1012.81
   928.9 1013.54  1098.0 1012.75  1149.1 1014.12  1171.9 1018.33  1241.7 1036.30
  1257.2 1039.24  1272.6 1040.32  1288.1 1044.18  1320.4 1056.92  1417.6 1092.33
#Mann= 3 , 0 , 0
       0     0.1       0   669.5   0.045       0   684.5     0.1       0
Bank Sta=   669.5,   684.5
Exp/Cntr=0.3,0.1

Type RM Length L Ch R = 1 ,76.6,65.099,76.617,88.134
XS GIS Cut Line= 4
     1695830.011      315265.221     1695591.985      315273.389
     1694831.236      315570.921     1694497.534      315947.795
#Sta/Elev= 30
       0 1107.19    28.9 1098.05   100.2 1079.39   112.1 1074.76   171.5 1047.69
   183.4 1043.26   207.1 1040.48   255.9 1027.96   268.6 1025.83   434.3 1018.76
   510.8 1012.07   549.1 1007.47   572.5 1005.85   599.9 1004.96   651.1 1005.00
   679.7 1004.23   682.5 1004.17   694.7 1004.51   714.8 1006.33   727.5 1006.74
   842.3 1004.91   956.1 1008.19  1055.0 1008.66  1103.2 1009.58  1217.8 1008.84
  1325.2 1011.34  1483.8 1012.89  1499.6 1013.72  1515.5 1015.76  1558.4 1025.25
#Mann= 3 , 0 , 0
       0     0.1       0   679.7   0.045       0   694.7     0.1       0
Bank Sta=   679.7,   694.7
Exp/Cntr=0.3,0.1